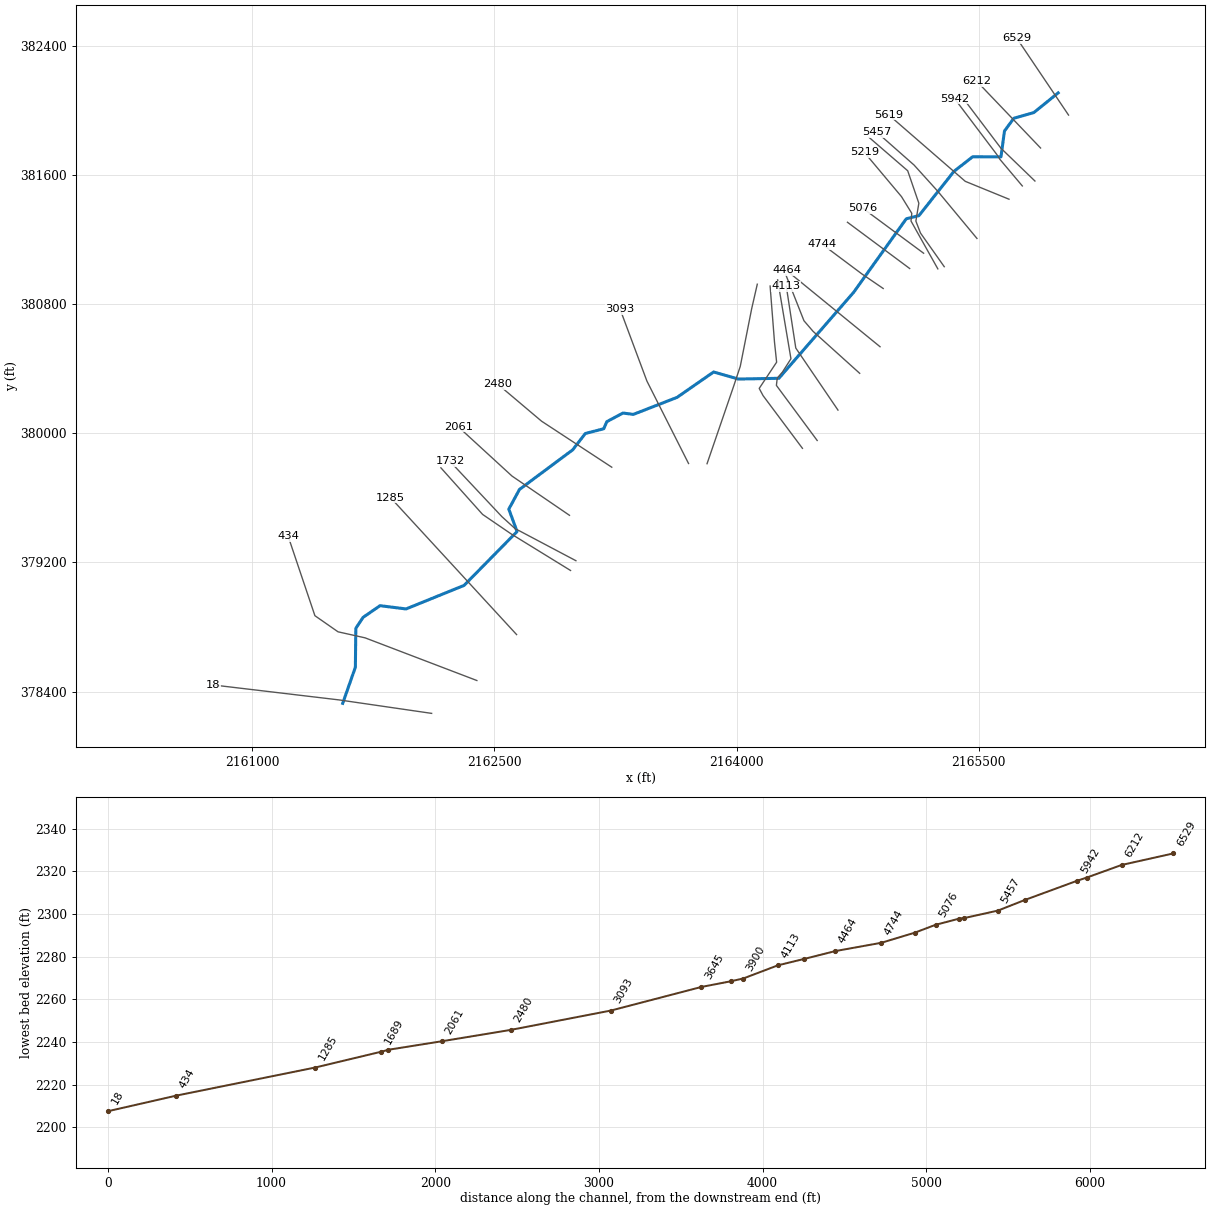
--- SPRINGCKT3.prj (project) ---

Proj Title=SPRINGCKT3
Current Plan=p01
Default Exp/Contr=0.3,0.1
English Units
Geom File=g01
Flow File=f01
Plan File=p01
Y Axis Title=Elevation
X Axis Title(PF)=Main Channel Distance
X Axis Title(XS)=Station
BEGIN DESCRIPTION:
Stream Name- Spring Creek Tributary 3
Flood Zone: Zone A
Greenbrier County, WV
County-Wide Study
WVDHSEM-2018-3, Flood Risk Project
HEC-RAS Version: 5.0.7
General Notes:
For the Hydrology Regression was used.
END DESCRIPTION:
DSS Export Rating Curves= 0
DSS Export Rating Curve Sorted= 0
DSS Export Volume Flow Curves= 0
DXF Filename=A3a.
DXF OffsetX= 0
DXF OffsetY= 0
DXF ScaleX= 1
DXF ScaleY= 10

--- SPRINGCKT3.p01 (plan) ---

Plan Title=Floodplain
Program Version=5.07
Short Identifier=Floodplain
Geom File=g01
Flow File=f01
Subcritical Flow
K Sum by GR= 0
Std Step Tol= 0.01
Critical Tol= 0.01
Num of Std Step Trials= 20
Max Error Tol= 0.3
Flow Tol Ratio= 0.001
Split Flow NTrial= 30
Split Flow Tol= 0.02
Split Flow Ratio= 0.02
Log Output Level= 0
Friction Slope Method= 1
Unsteady Friction Slope Method= 2
Unsteady Bridges Friction Slope Method= 1
Parabolic Critical Depth
Global Vel Dist= 0 , 0 , 0
Global Log Level= 0
CheckData=True
Encroach Param=-1 ,0,0, 0
Computation Interval=1MIN
Output Interval=1HOUR
Instantaneous Interval=1HOUR
Mapping Interval=1HOUR
Computation Time Step Use Courant=        0
Computation Time Step Use Time Series=    0
Computation Time Step Count To Double=0
Computation Time Step Max Doubling=0
Computation Time Step Max Halving=0
Computation Time Step Residence Courant=0
Run HTab= 0
Run UNet= 0
Run Sediment= 0
Run PostProcess= 0
Run WQNet= 0
Run RASMapper= 0
UNET Theta= 1
UNET Theta Warmup= 1
UNET ZTol= 0.02
UNET ZSATol= 0.02
UNET MxIter= 20
UNET Max Iter WO Improvement= 0
UNET MaxInSteps= 0
UNET DtIC= 0
UNET DtMin= 0
UNET MaxCRTS= 20
UNET WFStab= 2
UNET SFStab= 1
UNET WFX= 1
UNET SFX= 1
UNET 1D Methodology=Finite Difference
UNET DSS MLevel= 4
UNET Pardiso=0
UNET DZMax Abort= 100
UNET Use Existing IB Tables=-1
UNET Froude Reduction=False
UNET Froude Limit= 0.8
UNET Froude Power= 4
UNET D1 Cores= 0
UNET D2 Coriolis=0
UNET D2 Cores= 0
UNET D2 Theta= 1
UNET D2 Theta Warmup= 1
UNET D2 Z Tol= 0.01
UNET D2 Volume Tol= 0.01
UNET D2 Max Iterations= 20
UNET D2 Equation= 0
UNET D2 RampUpFraction=0.1
UNET D2 TimeSlices= 1
UNET D2 BCVolumeCheck=0
UNET D1D2 MaxIter= 0
UNET D1D2 ZTol=0.01
UNET D1D2 QTol=0.1
UNET D1D2 MinQTol=1
Write IC File= 0
Write IC File at Fixed DateTime=0
Write IC File at Sim End=0
Echo Input=False
Echo Parameters=False
Echo Output=False
Write Detailed= 0
HDF Write Warmup=0
HDF Write Time Slices=0
HDF Flush=0
HDF Face Node Velocities=0
HDF Compression= 1
HDF Chunk Size= 1
HDF Spatial Parts= 1
HDF Use Max Rows=0
HDF Fixed Rows= 1
Calibration Method= 0
Calibration Iterations= 20
Calibration Max Change=0.05
Calibration Tolerance=0.2
Calibration Maximum=1.5
Calibration Minimum=0.5
Calibration Optimization Method= 1
WQ AD Non Conservative
WQ ULTIMATE=-1
WQ Max Comp Step=1HOUR
WQ Output Interval=15MIN
WQ Output Selected Increments= 0
WQ Output face flow=0
WQ Output face velocity=0
WQ Output face area=0
WQ Output face dispersion=0
WQ Output cell volume=0
WQ Output cell surface area=0
WQ Output cell continuity=0
WQ Output cumulative cell continuity=0
WQ Output face conc=0
WQ Output face dconc_dx=0
WQ Output face courant=0
WQ Output face peclet=0
WQ Output face adv mass=0
WQ Output face disp mass=0
WQ Output cell mass=0
WQ Output cell source sink temp=0
WQ Output nsm pathways=0
WQ Output nsm derived pathways=0
WQ Output MaxMinRange=-1
WQ Daily Max Min Mean=-1
WQ Daily Range=0
WQ Daily Time=0
WQ Create Restart=0
WQ Fixed Restart=0
WQ System Summary=0
WQ Write To DSS=0
WQ Use Fixed Temperature=0
Sorting and Armoring Iterations= 10
XS Update Threshold= 0.02
Bed Roughness Predictor= 0
Hydraulics Update Threshold= 0.02
Energy Slope Method= 1
Volume Change Method= 1
Sediment Retention Method= 0
XS Weighting Method= 0
Number of US Weighted Cross Sections= 1
Number of DS Weighted Cross Sections= 1
Upstream XS Weight=0
Main XS Weight=1
Downstream XS Weight=0
Number of DS XS's Weighted with US Boundary= 1
Upstream Boundary Weight= 1
Weight of XSs Associated with US Boundary= 0
Number of US XS's Weighted with DS Boundary= 1
Downstream Boundary Weight= 0.5
Weight of XSs Associated with DS Boundary= 0.5
Percentile Method= 0
Sediment Output Level= 3
Mass or Volume Output= 0
Output Increment Type= 1
Profile and TS Output Increment= 1
XS Output Flag= 0
XS Output Increment= 10
Write Gradation File= 0
Read Gradation Hotstart= 0
Write HDF5 File= 1
Write Binary Output= 1
Write DSS Sediment File= 0
SV Curve= 0
Specific Gage Flag= 0

--- SPRINGCKT3.f01 (steady flow) ---

Flow Title=Flow
Program Version=5.07
Number of Profiles= 6
Profile Names=f1p,f10p,f4p,f2p,f02p,f1pplus
River Rch & RM=BEVERLYFK,Main            ,776
     323     167     225     272     456     478
River Rch & RM=BEVERLYFK,Main            ,220
     537     283     377     454     751     794
River Rch & RM=BOGGSRN,Main            ,1733
     558     295     392     472     780     825
River Rch & RM=DRYRN,Main            ,9301
     532     280     373     450     744     787
River Rch & RM=DRYRN,Main            ,8316
     594     314     418     503     829     878
River Rch & RM=DRYRN,Main            ,6862
     769     411     544     653    1070    1140
River Rch & RM=DRYRN,Main            ,5213
     898     483     637     763    1240    1330
River Rch & RM=DRYRN,Main            ,259
    1110     604     793     948    1540    1650
River Rch & RM=PNTHRCMPCK,Main            ,14558
     513     270     359     434     718     758
River Rch & RM=PNTHRCMPCK,Main            ,13060
     599     317     422     508     836     886
River Rch & RM=PNTHRCMPCK,Main            ,10150
     873     469     619     742    1210    1290
River Rch & RM=PNTHRCMPCK,Main            ,8160
     976     526     693     830    1350    1440
River Rch & RM=PNTHRCMPCK,Main            ,6420
    1080     588     772     923    1500    1600
River Rch & RM=RCKCMPRN,Main            ,4355
     581     307     409     492     812     860
River Rch & RM=RCKCMPRN,Main            ,1618
     692     368     488     586     963    1020
River Rch & RM=ROBBINSRN,Main            ,27789
     907     488     643     771    1260    1340
River Rch & RM=ROBBINSRN,Main            ,27014
    1170     638     837    1000    1620    1740
River Rch & RM=ROBBINSRN,Main            ,21785
    1330     728     953    1140    1830    1970
River Rch & RM=ROBBINSRN,Main            ,16781
    1830    1010    1320    1570    2500    2710
River Rch & RM=ROBBINSRN,Main            ,10962
    2050    1140    1480    1750    2790    3030
River Rch & RM=SPRINGCKT3,Main            ,6529
     583     309     410     494     815     863
River Rch & RM=SPRINGCKT3,Main            ,3093
     683     363     482     579     951    1010
River Rch & RM=SPRINGCKT3,Main            ,434
     860     462     609     730    1190    1270
Boundary for River Rch & Prof#=BEVERLYFK,Main            , 1
Up Type= 0
Dn Type= 3
Dn Slope=0.045649
Boundary for River Rch & Prof#=BEVERLYFK,Main            , 2
Up Type= 0
Dn Type= 3
Dn Slope=0.045649
Boundary for River Rch & Prof#=BEVERLYFK,Main            , 3
Up Type= 0
Dn Type= 3
Dn Slope=0.045649
Boundary for River Rch & Prof#=BEVERLYFK,Main            , 4
Up Type= 0
Dn Type= 3
Dn Slope=0.045649
Boundary for River Rch & Prof#=BEVERLYFK,Main            , 5
Up Type= 0
Dn Type= 3
Dn Slope=0.045649
Boundary for River Rch & Prof#=BEVERLYFK,Main            , 6
Up Type= 0
Dn Type= 3
Dn Slope=0.045649
Boundary for River Rch & Prof#=BOGGSRN,Main            , 1
Up Type= 0
Dn Type= 3
Dn Slope=0.043074
Boundary for River Rch & Prof#=BOGGSRN,Main            , 2
Up Type= 0
Dn Type= 3
Dn Slope=0.043074
Boundary for River Rch & Prof#=BOGGSRN,Main            , 3
Up Type= 0
Dn Type= 3
Dn Slope=0.043074
Boundary for River Rch & Prof#=BOGGSRN,Main            , 4
Up Type= 0
Dn Type= 3
Dn Slope=0.043074
Boundary for River Rch & Prof#=BOGGSRN,Main            , 5
Up Type= 0
Dn Type= 3
Dn Slope=0.043074
Boundary for River Rch & Prof#=BOGGSRN,Main            , 6
Up Type= 0
Dn Type= 3
Dn Slope=0.043074
Boundary for River Rch & Prof#=DRYRN,Main            , 1
Up Type= 0
Dn Type= 3
Dn Slope=0.021282
Boundary for River Rch & Prof#=DRYRN,Main            , 2
Up Type= 0
Dn Type= 3
Dn Slope=0.021282
Boundary for River Rch & Prof#=DRYRN,Main            , 3
Up Type= 0
Dn Type= 3
Dn Slope=0.021282
Boundary for River Rch & Prof#=DRYRN,Main            , 4
Up Type= 0
Dn Type= 3
Dn Slope=0.021282
Boundary for River Rch & Prof#=DRYRN,Main            , 5
Up Type= 0
Dn Type= 3
Dn Slope=0.021282
Boundary for River Rch & Prof#=DRYRN,Main            , 6
Up Type= 0
Dn Type= 3
Dn Slope=0.021282
Boundary for River Rch & Prof#=PNTHRCMPCK,Main            , 1
Up Type= 0
Dn Type= 3
Dn Slope=0.02712
Boundary for River Rch & Prof#=PNTHRCMPCK,Main            , 2
Up Type= 0
Dn Type= 3
Dn Slope=0.02712
Boundary for River Rch & Prof#=PNTHRCMPCK,Main            , 3
Up Type= 0
Dn Type= 3
Dn Slope=0.02712
Boundary for River Rch & Prof#=PNTHRCMPCK,Main            , 4
Up Type= 0
Dn Type= 3
Dn Slope=0.02712
Boundary for River Rch & Prof#=PNTHRCMPCK,Main            , 5
Up Type= 0
Dn Type= 3
Dn Slope=0.02712
Boundary for River Rch & Prof#=PNTHRCMPCK,Main            , 6
Up Type= 0
Dn Type= 3
Dn Slope=0.02712
Boundary for River Rch & Prof#=RCKCMPRN,Main            , 1
Up Type= 0
Dn Type= 3
Dn Slope=0.013802
Boundary for River Rch & Prof#=RCKCMPRN,Main            , 2
Up Type= 0
Dn Type= 3
Dn Slope=0.013802
Boundary for River Rch & Prof#=RCKCMPRN,Main            , 3
Up Type= 0
Dn Type= 3
Dn Slope=0.013802
Boundary for River Rch & Prof#=RCKCMPRN,Main            , 4
Up Type= 0
Dn Type= 3
Dn Slope=0.013802
Boundary for River Rch & Prof#=RCKCMPRN,Main            , 5
Up Type= 0
Dn Type= 3
Dn Slope=0.013802
Boundary for River Rch & Prof#=RCKCMPRN,Main            , 6
Up Type= 0
Dn Type= 3
Dn Slope=0.013802
Boundary for River Rch & Prof#=ROBBINSRN,Main            , 1
Up Type= 0
Dn Type= 3
Dn Slope=0.010317
Boundary for River Rch & Prof#=ROBBINSRN,Main            , 2
Up Type= 0
Dn Type= 3
Dn Slope=0.010317
Boundary for River Rch & Prof#=ROBBINSRN,Main            , 3
Up Type= 0
Dn Type= 3
Dn Slope=0.010317
Boundary for River Rch & Prof#=ROBBINSRN,Main            , 4
Up Type= 0
Dn Type= 3
Dn Slope=0.010317
Boundary for River Rch & Prof#=ROBBINSRN,Main            , 5
Up Type= 0
Dn Type= 3
Dn Slope=0.010317
Boundary for River Rch & Prof#=ROBBINSRN,Main            , 6
Up Type= 0
Dn Type= 3
Dn Slope=0.010317
Boundary for River Rch & Prof#=SPRINGCKT3,Main            , 1
Up Type= 0
Dn Type= 3
Dn Slope=0.016207
Boundary for River Rch & Prof#=SPRINGCKT3,Main            , 2
Up Type= 0
Dn Type= 3
Dn Slope=0.016207
Boundary for River Rch & Prof#=SPRINGCKT3,Main            , 3
Up Type= 0
Dn Type= 3
Dn Slope=0.016207
Boundary for River Rch & Prof#=SPRINGCKT3,Main            , 4
Up Type= 0
Dn Type= 3
Dn Slope=0.016207
Boundary for River Rch & Prof#=SPRINGCKT3,Main            , 5
Up Type= 0
Dn Type= 3
Dn Slope=0.016207
Boundary for River Rch & Prof#=SPRINGCKT3,Main            , 6
Up Type= 0
Dn Type= 3
Dn Slope=0.016207
DSS Import GetInterval= 0
DSS Import GetPeak= 0
DSS Import FillOption= 0

--- SPRINGCKT3.g01 (geometry) ---

Geom Title=Geometry
Program Version=5.07

River Reach=SPRINGCKT3      ,Main
Reach XY= 30
2165991.77881972382108.0262008162165841.07538097381986.171129555
2165716.95030114381950.8260558992165659.13086297381871.588025391
2165637.60334697381711.8655758052165462.60336889381712.560128227
2165346.63083181381622.2824216492165129.57188272381348.060529143
2165050.86141022381328.2154244782164725.33351797380873.259969562
2164261.98437905380340.4457464812164011.73520763380335.663603812
2163857.81195906380379.4125320612163631.37179513380222.204841226
2163360.45337372380116.7670599822163296.49746488380125.222095564
2163196.58034189380071.9636718932163177.21784781380027.891909644
2163063.12850906379998.463490814 2162985.1119328379897.401685059
2162655.29828797379651.8450895552162589.33811805379529.933916062
2162640.43512872379391.1333406422162312.05586421379057.565766305
2161952.88105763378911.865598395 2161791.7698313378932.004665732
2161686.90882055378859.7823692262161641.76980323378791.726731062
2161638.99224973378550.7544439732161560.55474256378327.178775638

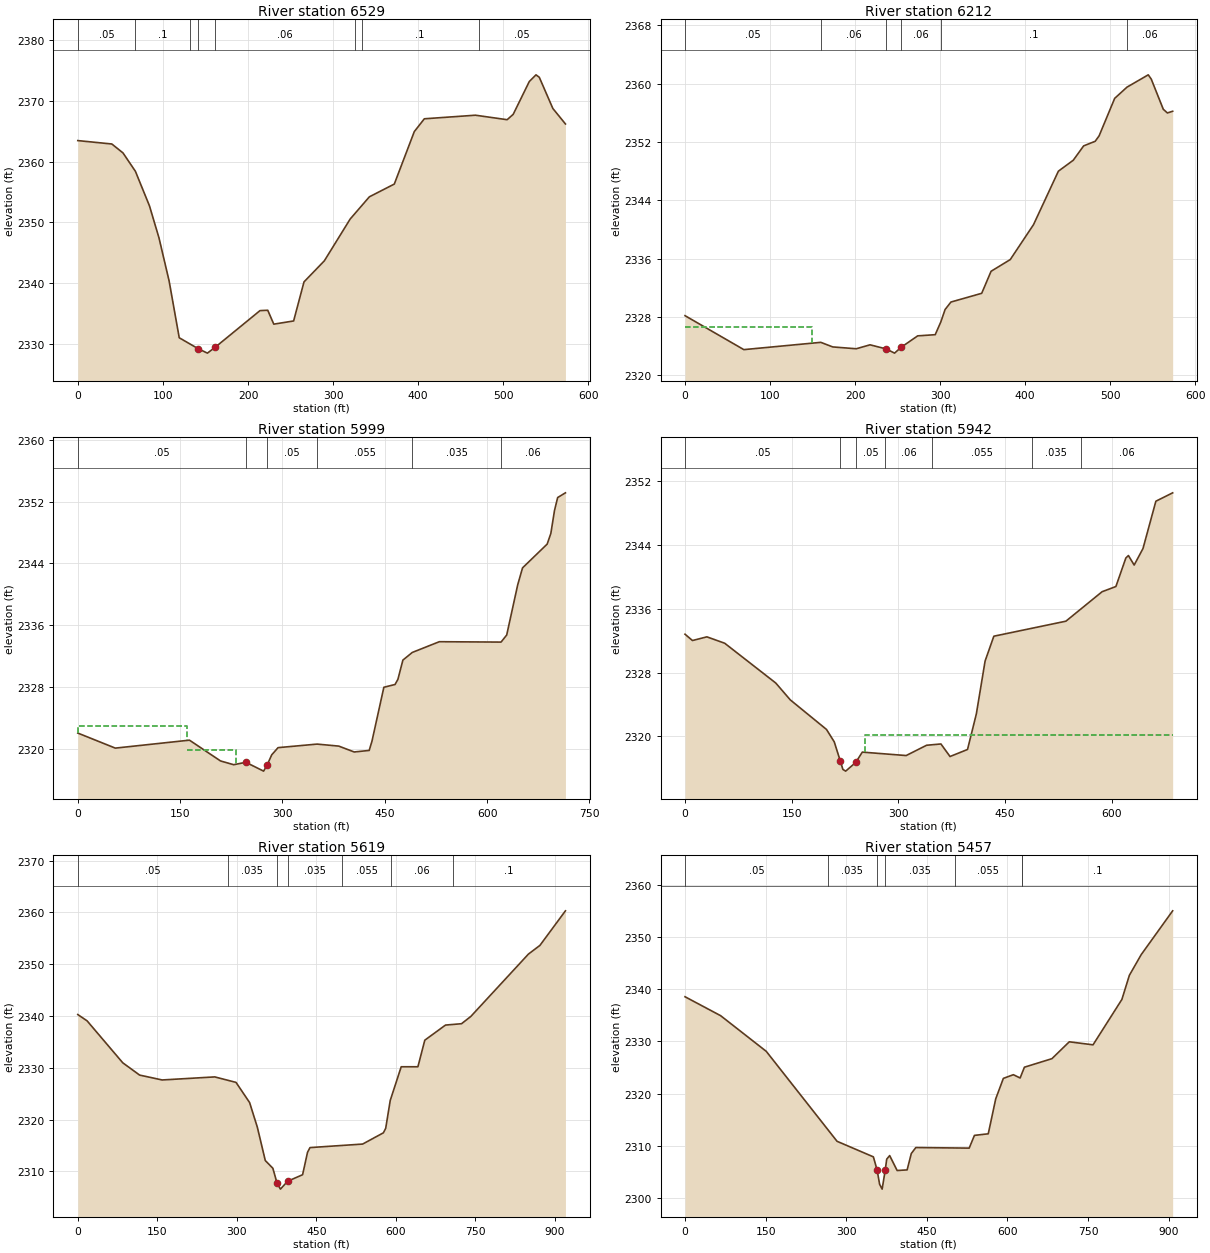
Type RM Length L Ch R = 1 ,6529    ,313.7,316.9,316.7
XS GIS Cut Line= 2
2166056.05723447381970.6829715672165735.96174605382445.943503976
#Sta/Elev= 30
       0 2363.47      40 2362.91    53.1 2361.44    67.7 2358.41    84.2 2352.73
    95.4 2347.45   107.3 2340.36   119.2    2331  141.272329.213   152.3 2328.47
  161.592329.453   214.1 2335.47   223.2 2335.53   230.3 2333.24   253.6 2333.77
   265.8  2340.2   289.7 2343.67   320.1 2350.56   342.6 2354.21   371.9 2356.31
   395.4 2364.95   407.2 2367.06   467.2 2367.65   504.5 2366.91   511.6 2367.79
   530.5 2373.19   538.4  2374.3   542.3 2373.89   558.2 2368.76     573 2366.21
#Mann= 8 ,-1 , 0
       0     .05       0   67.61      .1       0  132.17     .06       0
  141.27    .045       0  161.59     .06       0     326     .05       0
  333.48      .1       0  471.17     .05       0
Bank Sta=141.27,161.59
XS Rating Curve= 0 ,0
Exp/Cntr=0.3,0.1

Type RM Length L Ch R = 1 ,6212    ,218.8,213.6,213.1
XS GIS Cut Line= 2
2165882.80210475381766.6974576042165486.35989693 382181.25859631
#Sta/Elev= 30
       0 2328.18    69.2 2323.52   159.7 2324.52   173.8 2323.89   201.4 2323.64
   217.7 2324.18   236.62323.617   246.5 2323.04   254.1 2323.83   273.7 2325.41
   294.3 2325.57   300.9 2327.32   305.9 2329.02   312.8 2330.05     349 2331.25
     360 2334.27   382.6 2335.88   409.9 2340.66   439.2 2348.01   456.7 2349.51
   468.9 2351.48   482.5 2352.11   487.1 2352.86   505.4    2358   519.9 2359.54
   544.9 2361.23   548.4 2360.65   562.6  2356.5   567.4    2356   573.6 2356.23
#Mann= 6 ,-1 , 0
       0     .05       0   159.7     .06       0   236.6    .045       0
   254.1     .06       0   300.9      .1       0   519.9     .06       0
#XS Ineff= 2 , 0
          149.64 2326.62
Permanent Ineff=
       F       F
Bank Sta=236.6,254.1
XS Rating Curve= 0 ,0
Exp/Cntr(USF)=0,0
Exp/Cntr=0.5,0.3

Type RM Length L Ch R = 1 ,5999    ,56,56.8,53.6
XS GIS Cut Line= 3
2165847.96636534381562.1583528262165637.22367554381765.441124401
2165382.65396618382102.069934211
#Sta/Elev= 30
       0 2322.04      55 2320.09   163.7 2321.12   209.2 2318.43   228.6 2317.94
   246.32318.254   272.4 2317.11   277.6  2317.9   284.3 2319.22   293.6 2320.15
   350.8 2320.61   382.6 2320.35   405.2 2319.59   427.2 2319.79   431.3    2321
   448.7 2327.97   465.1 2328.33   469.3    2329   476.6 2331.49   490.4 2332.48
     530 2333.87   620.5 2333.82   628.8 2334.74   644.9 2341.23     652 2343.43
   688.1 2346.51   693.5 2347.89   698.9 2350.88   703.5 2352.54   714.9 2353.15
#Mann= 6 ,-1 , 0
       0     .05       0   246.3    .045       0   277.6     .05       0
   350.8    .055       0   490.4    .035       0   620.5     .06       0
#XS Ineff= 3 ,-1
       0     160    2323     160   231.3  2319.9   292.6     600  2319.9
Permanent Ineff=
       F       F       F
Bank Sta=246.3,277.6
XS Rating Curve= 0 ,0
Exp/Cntr(USF)=0,0
Exp/Cntr=0.5,0.3

Type RM Length L Ch R = 1 ,5942    ,317.9,322.7,323
XS GIS Cut Line= 4
2165769.72184914381531.721907228 2165630.8330193381696.652351648
2165611.30189039381727.0341806412165349.80011681382073.171283647
#Sta/Elev= 30
       0  2332.8    10.5 2332.01    30.8 2332.47    55.8 2331.67   127.6 2326.69
     148 2324.58   198.9 2320.88   209.8 2319.33  218.45 2316.89     222 2315.87
   225.9 2315.66  239.982316.746   249.3 2318.04   310.9 2317.61   339.7  2318.9
   359.8 2319.06   372.6 2317.49   397.2 2318.37   409.6 2322.82   421.9 2329.44
   434.2 2332.55   535.5 2334.43   586.4 2338.12   605.8 2338.77   619.8 2342.34
   623.4 2342.65   631.5 2341.46   643.9 2343.53     662 2349.45   685.6  2350.5
#Mann= 7 ,-1 , 0
       0     .05       0  218.45    .045       0  239.98     .05       0
   281.8     .06       0  346.98    .055       0  487.17    .035       0
  556.64     .06       0
#XS Ineff= 1 ,-1
  252.74  685.55 2320.23
Permanent Ineff=
       F
Bank Sta=218.45,239.98
XS Rating Curve= 0 ,0
Exp/Cntr=0.5,0.3

Type RM Length L Ch R = 1 ,5619    ,162.9,162.2,161.1
XS GIS Cut Line= 3
2165687.28369381381449.5278458892165416.45057406381560.204789892
2164942.49220438381971.663284555
#Sta/Elev= 30
       0 2340.27    17.5 2339.06    84.8 2330.96   116.7 2328.58   159.2 2327.64
   258.5 2328.23   298.6 2327.17   324.2 2323.28   338.8 2318.52   353.8 2312.08
   368.1 2310.59  375.912307.739   382.4 2306.56  395.952308.083   424.2 2309.34
   433.5 2313.67   438.2 2314.58   537.5 2315.26   576.6 2317.43     581 2318.29
   589.6 2323.69   610.3 2330.19   641.8 2330.19   654.8 2335.32   693.9 2338.24
   724.1  2338.5   741.7 2339.91   850.3 2351.94   872.1 2353.63   920.2  2360.3
#Mann= 7 ,-1 , 0
       0     .05       0  282.67    .035       0  375.91    .045       0
  395.95    .035       0  499.05    .055       0  590.58     .06       0
  707.38      .1       0
Bank Sta=375.91,395.95
XS Rating Curve= 0 ,0
Exp/Cntr=0.3,0.1

Type RM Length L Ch R = 1 ,5457    ,217.3,205,194.2
XS GIS Cut Line= 4
2165488.81000939381206.5106153942165246.62250164381498.177354887
2165099.48729722381660.937528059 2164867.7164353381865.364612639
#Sta/Elev= 30
       0  2338.6    66.3 2334.96   151.2 2328.11     283 2310.82   350.6 2307.83
  357.532305.292   362.2 2302.56   366.9 2301.63  372.572305.236   375.4 2307.38
   380.9 2308.08   394.8 2305.21   413.4 2305.32   421.2 2308.48   429.6 2309.62
   528.9 2309.51   538.7 2311.96   564.4 2312.26   578.3 2318.98   592.5 2322.91
   611.1 2323.62   623.7 2322.99   631.7 2325.06   682.9  2326.7   715.2 2329.94
   759.4 2329.36   813.1 2338.08     827 2342.71   849.1  2346.7   907.6 2355.11
#Mann= 7 ,-1 , 0
       0     .05       0  265.66    .035       0  357.53    .045       0
  372.57    .035       0  501.71    .055       0  626.57     .06       0
  626.96      .1       0
Bank Sta=357.53,372.57
XS Rating Curve= 0 ,0
Exp/Cntr=0.5,0.3

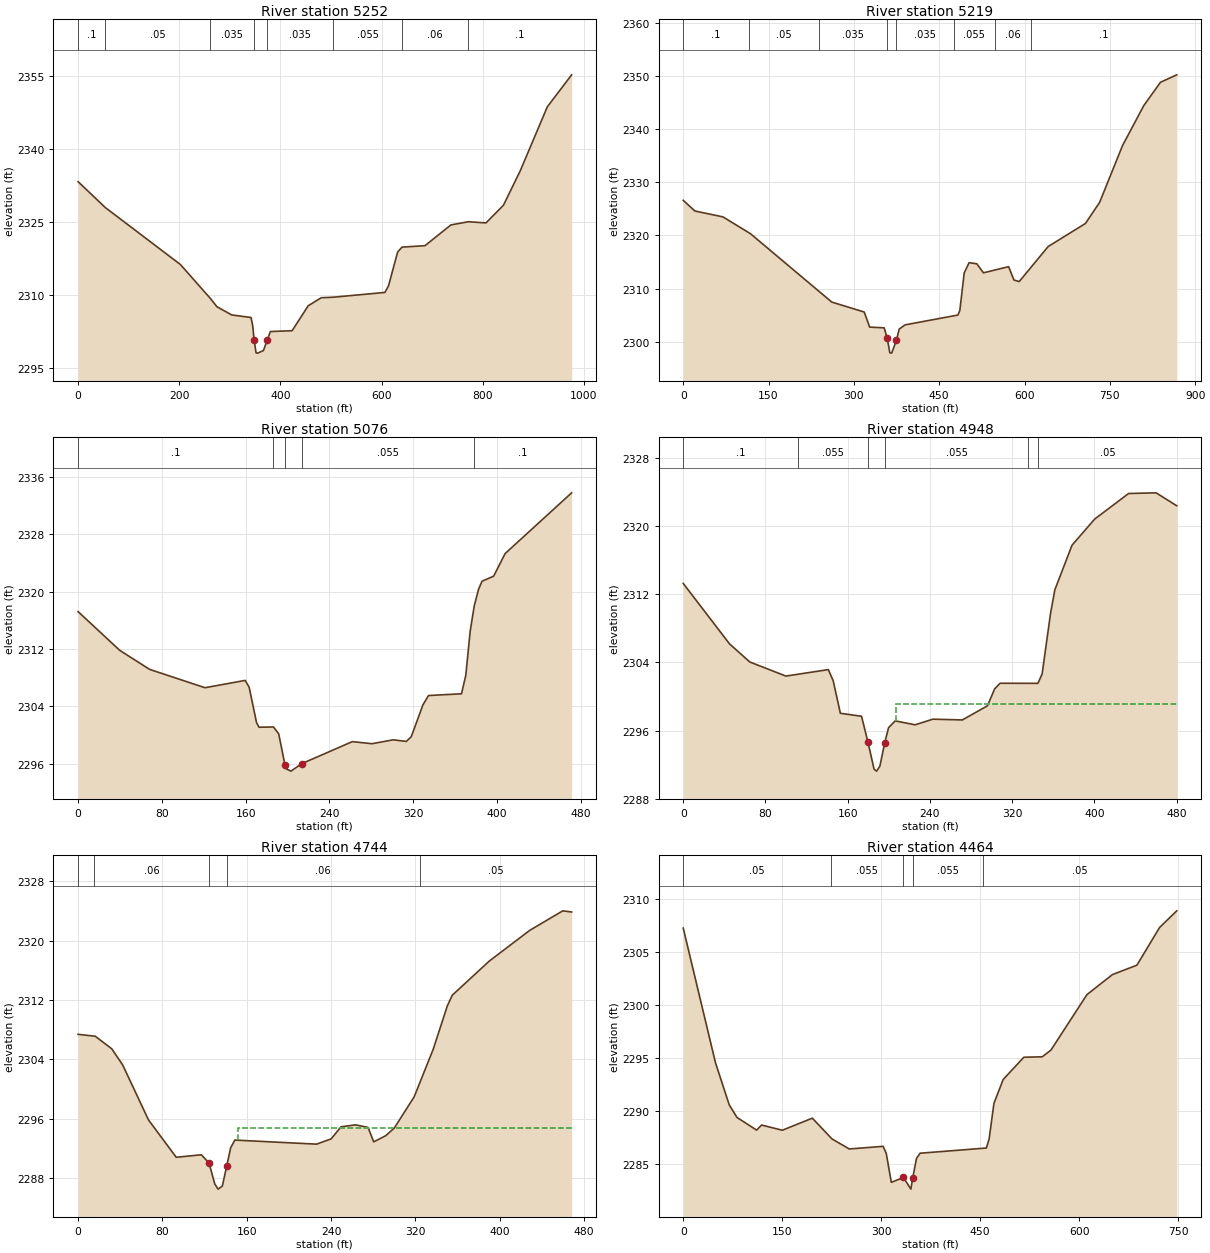
Type RM Length L Ch R = 1 ,5252    ,29.9,32.8,36.6
XS GIS Cut Line= 6
2165286.24217306381031.5588655622165139.10664055381239.892438397
2165110.46070047381314.111121982 2165128.8635508381424.649286732
2165059.83875448381625.7922571452164821.12335263381831.955558732
#Sta/Elev= 30
       0 2333.33    53.7 2328.03   202.3 2316.33   261.6 2309.36   274.6 2307.66
   303.8 2305.98     342 2305.45   345.3 2303.74  348.14 2300.81   351.9  2298.2
   355.2 2298.14   366.5 2298.68  374.092300.813   380.2 2302.57   423.2 2302.74
   455.1 2307.87   480.9 2309.51     505 2309.62   606.7  2310.6   613.8 2311.94
   631.8 2318.88   640.5  2319.9   685.9 2320.19   737.1 2324.45   771.8 2325.11
   806.5 2324.86   841.1  2328.5   874.3 2335.56   927.8 2348.69   975.9 2355.26
#Mann= 8 ,-1 , 0
       0      .1       0    53.7     .05       0   261.6    .035       0
  348.14    .045       0  374.09    .035       0     505    .055       0
   640.5     .06       0   771.8      .1       0
#XS Ineff= 2 , 0
             338  2302.5     384          2302.5
Permanent Ineff=
       F       F
Bank Sta=348.14,374.09
XS Rating Curve= 0 ,0
Exp/Cntr=0.5,0.3

Type RM Length L Ch R = 1 ,5219    ,135.7,143.6,151.9
XS GIS Cut Line= 5
2165246.47059906381018.1533805582165080.41154797381314.257775232
2165085.09920263381362.1746741382165021.36212538381465.625254646
2164790.89342622381740.364534557
#Sta/Elev= 30
       0 2326.61    20.5  2324.6    69.9 2323.49   118.3 2320.32   261.2 2307.45
   318.2 2305.58   327.8 2302.74   353.3  2302.6  358.75 2300.61   363.2 2297.93
   366.5 2297.84   374.82300.257   379.7 2302.36     390 2303.16   482.9 2305.01
   486.3 2305.87     494 2312.94   502.6 2314.87   516.2 2314.66   527.8 2312.96
   572.1 2314.12   581.4 2311.61   590.7 2311.31   641.6 2317.91   707.1 2322.25
   732.1 2326.23   772.3 2336.91   809.6 2344.43   839.1 2348.84   867.7 2350.24
#Mann= 8 ,-1 , 0
       0      .1       0  115.28     .05       0  238.36    .035       0
  358.75    .045       0   374.8    .035       0  475.37    .055       0
  547.57     .06       0  611.16      .1       0
Bank Sta=358.75,374.8
XS Rating Curve= 0 ,0
Exp/Cntr=0.5,0.3

Type RM Length L Ch R = 1 ,5076    ,127.9,127.9,127.8
XS GIS Cut Line= 2
2165158.44014328381115.0090879542164779.39704812381395.343043753
#Sta/Elev= 30
       0 2317.23    39.7 2311.83    68.3 2309.16   121.2  2306.6   159.6 2307.62
   163.4 2306.67   170.4 2301.75   172.8 2301.08   186.6 2301.12   191.6 2300.17
   197.62295.821   198.9 2295.26   203.3 2294.95   213.62295.989   261.9 2299.07
   280.7 2298.78   300.9 2299.32   313.5  2299.1   318.2 2299.75   329.4 2304.21
   334.7 2305.51   366.2 2305.75   370.3 2308.33   374.5  2314.5   378.4 2318.04
   382.5 2320.35   385.8 2321.47   396.9 2322.18   407.9 2325.34   471.4 2333.82
#Mann= 5 ,-1 , 0
       0      .1       0   186.6    .055       0   197.6    .045       0
   213.6    .055       0   378.4      .1       0
Bank Sta=197.6,213.6
XS Rating Curve= 0 ,0
Exp/Cntr(USF)=0,0
Exp/Cntr=0.3,0.1

Type RM Length L Ch R = 1 ,4948    ,202.8,203.4,203.6
XS GIS Cut Line= 2
2165072.14351989381020.3124969752164686.72663981381306.770913556
#Sta/Elev= 30
       0 2313.24    45.1 2306.15    64.8 2304.03    99.9 2302.38   141.2 2303.14
   145.9 2301.84   152.9 2298.02   173.5 2297.67  179.672294.665   185.7 2291.47
   188.1 2291.24   191.3 2291.81  196.012294.539   199.8 2296.34   206.2 2297.13
   225.6 2296.67   242.9 2297.33   271.6 2297.24     296  2298.9     303 2300.88
   308.3 2301.54   345.1 2301.53   349.2 2302.63   357.4 2309.74   361.6  2312.5
   378.3 2317.72   400.3 2320.78   433.3 2323.78   460.1 2323.86   480.2 2322.34
#Mann= 6 ,-1 , 0
       0      .1       0  111.91    .055       0  179.67    .045       0
  196.01    .055       0  335.68     .06       0   345.1     .05       0
#XS Ineff= 2 , 0
                          206.56          2299.1
Permanent Ineff=
       F       F
Bank Sta=179.67,196.01
XS Rating Curve= 0 ,0
Exp/Cntr=0.3,0.1

Type RM Length L Ch R = 1 ,4744    ,281.6,280.8,280.2
XS GIS Cut Line= 3
2164908.08085589380896.6145816452164776.57062022380986.458562061
2164529.17478955381171.354189649
#Sta/Elev= 30
       0 2307.38    16.3 2307.12      32 2305.42    42.3 2303.25    66.8 2295.84
    93.1 2290.81   116.9 2291.15  124.232290.038   129.6 2287.23   132.8 2286.52
   136.8 2286.93  141.052289.671   144.7 2292.09   148.7 2293.13   226.2 2292.58
     240 2293.29   249.4 2294.92   263.1 2295.18     275 2294.84   280.4 2292.89
   291.7 2293.71   299.9 2294.75   318.8 2298.97   336.8 2305.36   350.2 2311.21
   354.9 2312.65     390 2317.25   428.4 2321.39   459.7 2324.02   468.1 2323.86
#Mann= 5 ,-1 , 0
       0     .05       0   15.26     .06       0  124.23    .045       0
  141.05     .06       0  324.02     .05       0
#XS Ineff= 2 , 0
                          151.39         2294.76
Permanent Ineff=
       F       F
Bank Sta=124.23,141.05
XS Rating Curve= 0 ,0
Exp/Cntr=0.3,0.1

Type RM Length L Ch R = 1 ,4464    ,190.7,190.3,190.1
XS GIS Cut Line= 2
2164888.54972698380535.9374814782164309.12273622381008.594016477
#Sta/Elev= 30
       0 2307.27    48.9 2294.55    69.7 2290.59    81.4  2289.4   111.2  2288.2
   118.7 2288.68   150.2 2288.19   195.6 2289.33   225.4 2287.37   251.6 2286.42
   302.9 2286.67   307.6 2286.01   315.3 2283.27  333.73 2283.73   344.9 2282.63
  347.642283.656   353.4 2285.52   358.9 2286.02   459.3 2286.51   463.5 2287.37
   470.8 2290.73   484.8 2292.98   516.1 2295.08   543.9 2295.12   557.1 2295.75
   611.7 2300.99   650.3 2302.88   687.4 2303.77   721.8 2307.33   747.8  2308.9
#Mann= 5 ,-1 , 0
       0     .05       0  224.39    .055       0  333.73    .045       0
  347.64    .055       0  453.76     .05       0
Bank Sta=333.73,347.64
XS Rating Curve= 0 ,0
Exp/Cntr=0.3,0.1

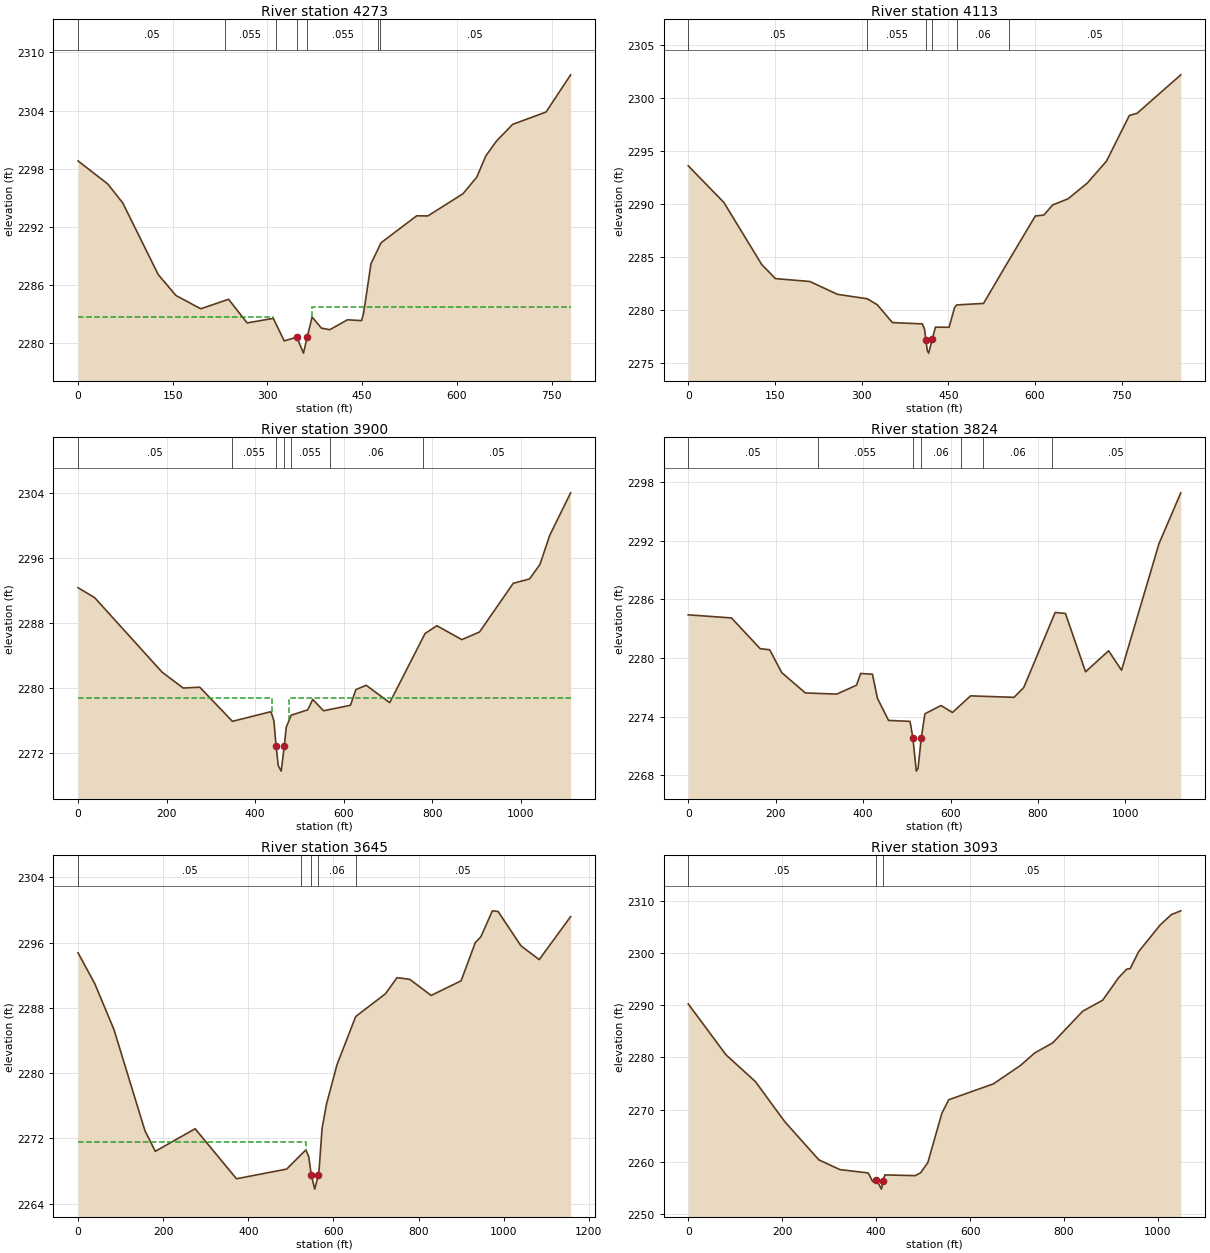
Type RM Length L Ch R = 1 ,4273    ,161.4,160.1,158.8
XS GIS Cut Line= 4
2164762.41021547380371.2202912272164473.34780148380631.637093231
2164417.35841213380696.741293728 2164305.3789773380980.595384806
#Sta/Elev= 30
       0  2298.8    47.2 2296.41    70.8 2294.46     127 2287.06   155.1  2284.9
   194.3 2283.53   238.4 2284.51   267.8 2282.07   309.2 2282.54   326.6 2280.21
  346.412280.607     357 2278.95  362.91 2280.59   370.7 2282.68   385.4 2281.53
   398.7 2281.37   426.7 2282.39     449 2282.31   452.3  2283.1   463.9 2288.18
   479.9 2290.35   536.3 2293.13     554 2293.12   609.7 2295.41   631.6 2297.14
   645.7 2299.31   662.8 2300.86   688.2 2302.57   741.2 2303.85   780.1 2307.69
#Mann= 7 ,-1 , 0
       0     .05       0  232.64    .055       0  313.27     .06       0
  346.41    .045       0  362.91    .055       0  475.34     .06       0
  477.82     .05       0
#XS Ineff= 2 ,-1
       0  308.77 2282.65  371.25  780.08 2283.75
Permanent Ineff=
       F       F
Bank Sta=346.41,362.91
XS Rating Curve= 0 ,0
Exp/Cntr=0.3,0.1

Type RM Length L Ch R = 1 ,4113    ,223,213,210.2
XS GIS Cut Line= 3
2164627.98981636380143.4664398322164366.71989933380527.686906047
2164307.80609451380910.626637374
#Sta/Elev= 30
       0 2293.64    61.7 2290.18   127.2 2284.32     151 2282.99   210.4 2282.72
   258.1 2281.51   309.7 2281.09     327 2280.53   353.3 2278.84   404.9 2278.72
   408.9 2278.22   411.2 2277.18   413.5 2276.23   415.9 2275.96   422.42277.309
   427.7 2278.41   451.3  2278.4   460.8 2280.26   464.6 2280.51   510.9 2280.65
   554.1 2284.66   600.5  2288.9   615.3 2288.99   630.4 2289.94     657 2290.52
   690.1 2291.99   723.4 2294.06   763.2 2298.39   776.5 2298.59   852.1 2302.22
#Mann= 6 ,-1 , 0
       0     .05       0   309.7    .055       0   411.2    .045       0
   422.4    .055       0   464.6     .06       0   554.1     .05       0
Bank Sta=411.2,422.4
XS Rating Curve= 0 ,0
Exp/Cntr(USF)=0,0
Exp/Cntr=0.5,0.3

Type RM Length L Ch R = 1 ,3900    ,79.1,76.2,71.4
XS GIS Cut Line= 6
2164499.22668672379955.2083279792164246.62253314380296.354299232
2164251.89614464380341.8548643892164283.84030648380378.660565063
 2164336.7148536380461.3130966932164254.39166192380950.135320277
#Sta/Elev= 30
       0 2292.33    37.5 2291.11   189.6 2281.95   237.5 2279.98     275 2280.08
   348.8 2275.88   435.9 2277.07   442.5 2275.95  447.392272.856   452.4 2270.43
     459 2269.75  465.872272.788   470.3 2275.13   481.5 2276.63     519  2277.3
   530.3 2278.58   554.6 2277.18   615.5 2277.86   627.7 2279.78     651 2280.32
   704.2 2278.18     784 2286.69   810.6 2287.65   867.1 2285.94   907.1 2286.88
   983.2 2292.87  1020.1 2293.41  1043.6 2295.19  1065.6 2298.77  1112.9 2304.01
#Mann= 7 ,-1 , 0
       0     .05       0   348.8    .055       0  447.39    .045       0
  465.87     .06       0   481.5    .055       0   568.4     .06       0
     779     .05       0
#XS Ineff= 2 , 0
           437.3  2278.7   475.8          2278.7
Permanent Ineff=
       F       F
Bank Sta=447.39,465.87
XS Rating Curve= 0 ,0
Exp/Cntr=0.5,0.3

Type RM Length L Ch R = 1 ,3824    ,176.8,179,182.3
XS GIS Cut Line= 6
2164407.97227605379906.6116403942164164.04887939380233.000751391
2164140.14499359380277.7666225852164248.07337325380440.162533968
2164234.82452684380564.9107993812164207.69672042380911.693890807
#Sta/Elev= 30
       0 2284.43      99 2284.11   164.8 2280.96   186.3 2280.86     214 2278.52
   267.8 2276.44   339.7 2276.32     385 2277.23   394.4 2278.43   421.5 2278.35
   432.8 2275.89   458.2 2273.63   507.3 2273.53   513.8 2271.87   521.7 2268.44
   525.7 2268.73   533.1 2271.85   541.4 2274.31   578.3 2275.15   604.4 2274.44
   645.8 2276.14   745.3 2275.99   767.4 2276.99   839.3 2284.67   862.8 2284.57
   908.8  2278.6   961.5 2280.75   991.1 2278.76  1076.6 2291.69  1126.6 2296.91
#Mann= 7 ,-1 , 0
       0     .05       0  296.29    .055       0   513.8    .045       0
   533.1     .06       0  623.91     .05       0  674.42     .06       0
  831.15     .05       0
Bank Sta=513.8,533.1
XS Rating Curve= 0 ,0
Exp/Cntr=0.5,0.3

Type RM Length L Ch R = 1 ,3645    ,543.6,552,557.2
XS GIS Cut Line= 5
2163817.09780164379811.3247574722163983.76446305380297.001607642
2164022.82704897380414.1893653872164093.13957238380769.657814562
2164128.29567005380923.303832725
#Sta/Elev= 30
       0 2294.76    39.2 2290.98    84.3 2285.36   157.1 2272.96   181.4 2270.42
     275 2273.19   372.2 2267.06   490.1 2268.25   535.1  2270.6     542 2269.73
  547.632267.582   555.9 2265.79  564.132267.463   566.2 2268.17   573.2 2273.23
   583.5 2276.19   608.3 2281.05   652.2 2286.95   722.4 2289.75   749.2 2291.71
   779.3  2291.5   829.4 2289.53   899.7 2291.32   933.1 2296.01   946.1 2296.71
   973.2  2299.9   986.6 2299.82  1040.4 2295.61  1083.2 2293.92    1157 2299.19
#Mann= 5 ,-1 , 0
       0     .05       0   524.5     .06       0  547.63    .045       0
  564.13     .06       0  651.69     .05       0
#XS Ineff= 2 , 0
          535.82 2271.51
Permanent Ineff=
       F       F
Bank Sta=547.63,564.13
XS Rating Curve= 0 ,0
Exp/Cntr=0.3,0.1

Type RM Length L Ch R = 1 ,3093    ,606.6,613,615.9
XS GIS Cut Line= 3
2163702.51436938379812.6265921442163444.70189288380323.043222234
2163278.03523147380769.657814562
#Sta/Elev= 30
       0 2290.28    80.5  2280.5     143 2275.37   205.4 2267.69   278.1 2260.35
   323.1 2258.47   383.1 2257.84   392.8 2256.16  400.542256.575   411.3 2254.73
  414.992256.307   418.6 2257.46   483.2 2257.32   494.6 2257.86   510.1 2259.83
   539.9 2269.28   554.6 2271.88   649.7 2274.93   706.8 2278.43   737.5 2280.85
   776.1 2282.81   839.6 2288.86   882.2 2290.98   916.1 2295.29   933.2 2296.93
   940.9 2297.05   958.7 2300.29  1004.6 2305.41  1028.2  2307.4  1048.5 2308.13
#Mann= 3 ,-1 , 0
       0     .05       0  400.54    .045       0  414.99     .05       0
Bank Sta=400.54,414.99
XS Rating Curve= 0 ,0
Exp/Cntr=0.3,0.1

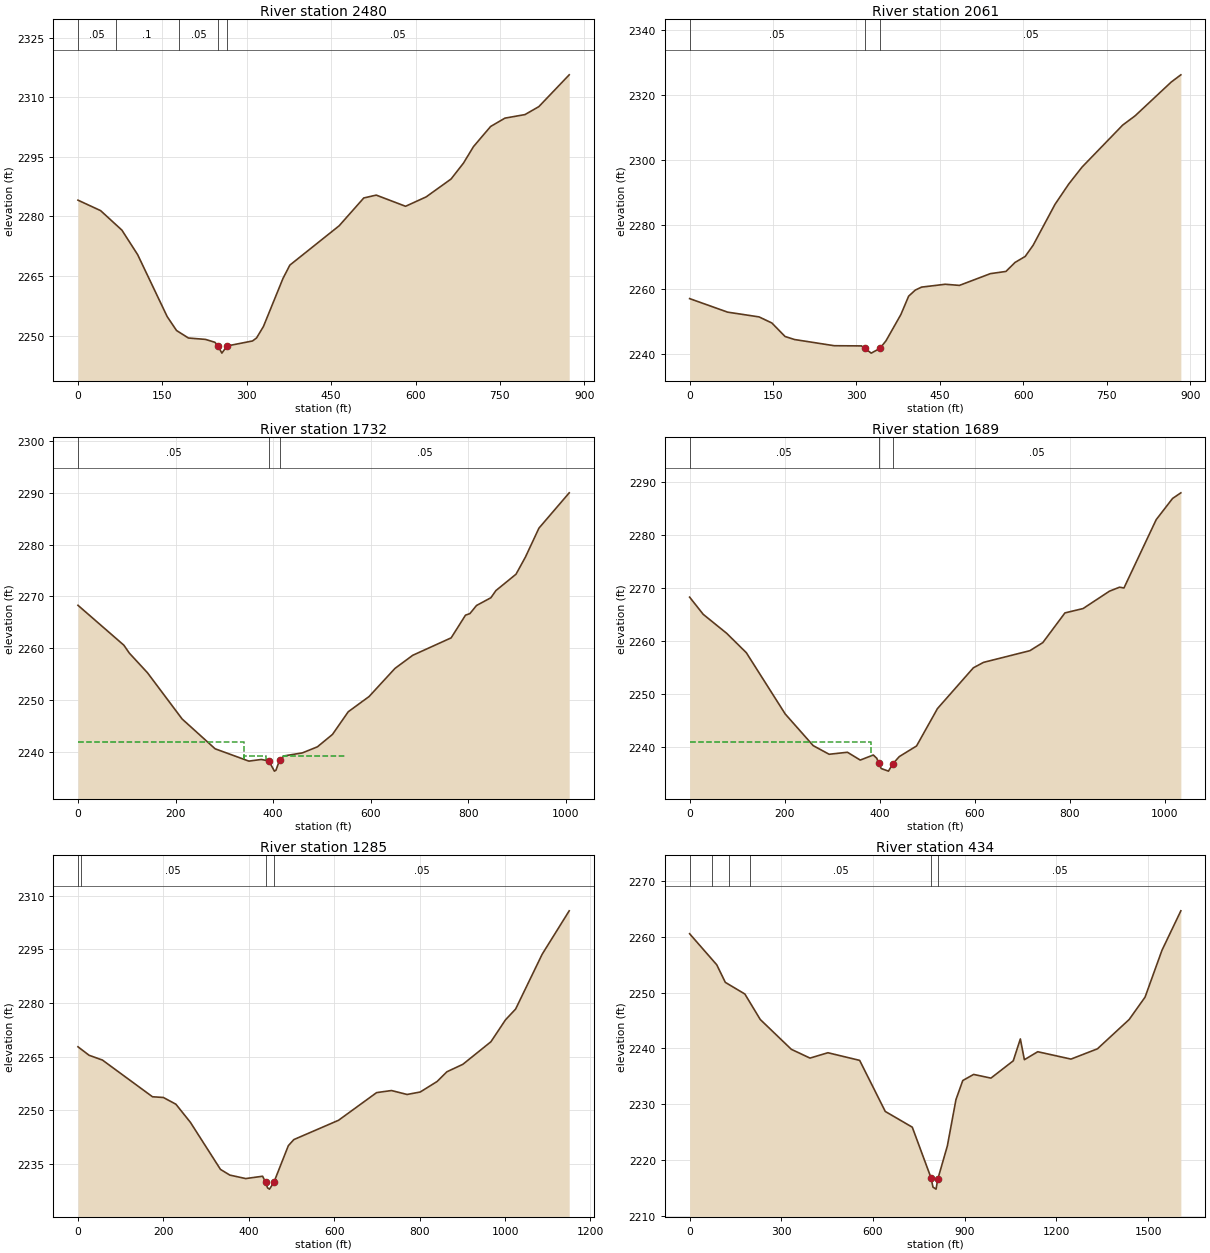
Type RM Length L Ch R = 1 ,2480    ,416.6,418.8,417.8
XS GIS Cut Line= 3
2163227.03697389379789.6233573112162792.14119014 380074.77961114
2162522.34973498 380302.64398481
#Sta/Elev= 30
       0  2284.1    40.2 2281.47    78.1 2276.56   106.1 2270.39   158.6 2254.81
   175.2 2251.32   196.3 2249.43   226.8 2249.08   243.4 2248.36  248.582247.487
   255.8 2245.63  265.01 2247.43   310.3 2248.69   317.4 2249.44   329.7 2252.34
   364.4 2264.41   376.6 2267.76   464.3 2277.66     508 2284.65   530.2 2285.37
   582.3 2282.56   618.9 2284.92   663.2 2289.42   685.3 2293.43     703 2297.56
   733.5 2302.63     759 2304.73   794.6 2305.62   819.2 2307.62   873.2 2315.62
#Mann= 5 ,-1 , 0
       0     .05       0   66.75      .1       0  179.27     .05       0
  248.58    .045       0  265.01     .05       0
Bank Sta=248.58,265.01
XS Rating Curve= 0 ,0
Exp/Cntr=0.3,0.1

Type RM Length L Ch R = 1 ,2061    ,328,329.5,331.5
XS GIS Cut Line= 3
2162965.05783905379491.7932443172162609.15500756379734.848860562
2162275.82168472380040.404351816
#Sta/Elev= 30
       0 2257.17    68.3 2252.99   124.8 2251.52   147.8 2249.65   171.6 2245.47
   188.6 2244.53     260 2242.62     309 2242.56   314.6 2241.86   326.5 2240.33
     342 2241.78     353 2244.12   379.8 2252.24   393.8 2257.93   405.7  2259.8
     417 2260.72   459.6  2261.6   485.1 2261.25   540.7 2264.88   568.7 2265.56
     585 2268.33   603.3 2270.19   617.5 2273.62   656.9 2286.27   681.5 2292.53
   705.6  2297.8   778.6 2310.76   800.9 2313.62   865.9 2324.06   883.2 2326.29
#Mann= 3 , 0 , 0
       0     .05       0   314.6    .045       0     342     .05       0
Bank Sta=314.6,342
XS Rating Curve= 0 ,0
Exp/Cntr=0.5,0.3

Type RM Length L Ch R = 1 ,1732    ,44,42.6,43.6
XS GIS Cut Line= 5
2163004.98853347379210.5434787272162653.48398714379396.423028231
2162630.91447847379406.8396740562162546.71287522379483.228628889
2162224.66430672379826.110489056
#Sta/Elev= 30
       0 2268.29    94.1 2260.59   105.3 2259.06   142.4 2255.28   213.4 2246.36
     281 2240.61   350.2 2238.23   375.7 2238.55  391.112238.259   402.5  2236.3
   405.7 2236.47  413.162238.446   422.5 2239.24   459.5 2239.81   490.5 2240.98
   521.5 2243.38   553.8 2247.75   596.5 2250.69   649.6 2256.12     686 2258.65
   764.7 2262.01   794.1 2266.39   803.1 2266.69   816.6 2268.25   846.1 2269.75
   856.4 2271.13   897.6 2274.29   916.8 2277.58   944.6 2283.18  1006.6 2289.99
#Mann= 3 ,-1 , 0
       0     .05       0  391.11    .045       0  413.16     .05       0
#XS Ineff= 3 ,-1
       0     340    2242     340   386.1  2239.3   419.1     550  2239.3
Permanent Ineff=
       F       F       F
Bank Sta=391.11,413.16
XS Rating Curve= 0 ,0
Exp/Cntr=0.5,0.3

Type RM Length L Ch R = 1 ,1689    ,407.4,403.5,399.8
XS GIS Cut Line= 4
2162971.62606739379150.1121691472162604.87286389379375.806599647
2162426.92144814379497.3345718092162168.67491739379785.962931558
#Sta/Elev= 30
       0 2268.31    28.7 2265.05    77.8 2261.48   119.3  2257.8   201.1 2246.21
     260 2240.22   293.5 2238.59     332 2238.97     359 2237.49   386.4 2238.45
   393.7 2237.83  398.012236.857   403.1 2235.89   418.3  2235.4  427.372236.772
   441.1 2238.15   477.4 2240.16   521.4 2247.23   596.9 2254.94   618.2 2255.97
   715.8 2258.18     743 2259.71   789.6 2265.33   827.7 2266.15   883.1 2269.43
   904.4 2270.19   913.7 2270.04   981.5 2282.96  1015.9 2286.97  1033.4 2288.04
#Mann= 3 ,-1 , 0
       0     .05       0  398.01    .045       0  427.37     .05       0
#XS Ineff= 2 , 0
          382.34 2240.85
Permanent Ineff=
       F       F
Bank Sta=398.01,427.37
XS Rating Curve= 0 ,0
Exp/Cntr=0.5,0.3

Type RM Length L Ch R = 1 ,1285    ,840.5,851.3,855.7
XS GIS Cut Line= 2
2162637.47909789378753.1395379012161858.39929122379599.493816316
#Sta/Elev= 30
       0 2267.74      26 2265.37    57.2 2264.04   174.5 2253.78   199.9 2253.58
   229.3  2251.7   263.3 2246.63   333.7 2233.49   355.6  2231.9   392.8 2230.93
   432.3 2231.58  439.162229.975   443.9 2228.33   448.5 2227.98  458.822229.904
   492.6 2240.12   505.5 2241.82   610.1 2247.21   699.3 2254.94   734.1 2255.52
   770.7 2254.42   801.4 2255.11   840.9 2258.04   863.9 2260.76   901.3 2262.85
   966.9 2269.14  1001.1 2275.27  1024.8 2278.28    1087  2293.6  1150.3 2305.72
#Mann= 4 ,-1 , 0
       0    .055       0    7.24     .05       0  439.16    .045       0
  458.82     .05       0
Bank Sta=439.16,458.82
XS Rating Curve= 0 ,0
Exp/Cntr=0.3,0.1

Type RM Length L Ch R = 1 ,434     ,413.9,415.7,415.7
XS GIS Cut Line= 5
2162391.51567905378468.5475873952161699.11089589378732.884985223
2161531.57612596378770.2113541362161388.34708172378870.037598059
2161222.49078614379362.283004642
#Sta/Elev= 30
       0 2260.55    88.8 2254.98   116.8 2251.83   180.7 2249.74   231.1 2245.17
   332.8 2239.82   393.8 2238.25   452.3 2239.21   556.2 2237.84     640 2228.68
   728.3 2225.86  789.72 2216.76     796 2215.11   806.1 2214.75  811.752216.538
   843.1 2222.51   871.2 2230.81   893.5 2234.23     929 2235.32   985.6 2234.66
  1058.6 2237.76  1081.8 2241.69    1095 2237.96  1138.7 2239.39  1247.4 2238.07
  1333.9 2239.91  1437.7 2245.17  1489.7 2249.18    1545 2257.58  1606.8 2264.66
#Mann= 6 ,-1 , 0
       0      .1       0   72.86     .05       0  129.78      .1       0
  196.66     .05       0  789.72    .045       0  811.75     .05       0
Bank Sta=789.72,811.75
XS Rating Curve= 0 ,0
Exp/Cntr=0.3,0.1

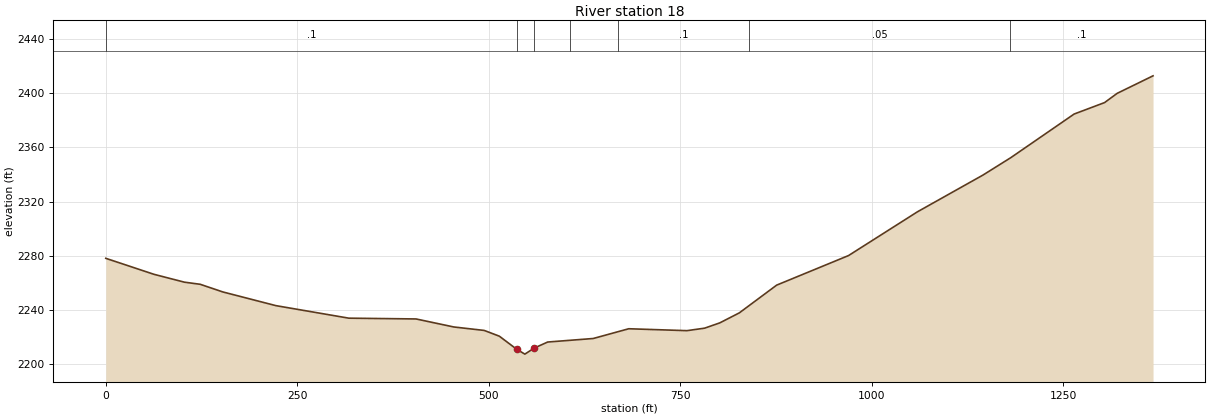
Type RM Length L Ch R = 1 ,18      ,18.54,18,16.32
XS GIS Cut Line= 3
 2162111.3794283378265.0607896452161538.46292321378348.394284397
2160755.88181122378441.276316479
#Sta/Elev= 30
       0 2278.15      63 2266.33   102.7 2260.54   123.2 2258.99   152.8 2253.34
   222.1 2243.23   317.2 2233.99     405 2233.41   454.2  2227.5     494 2224.94
   513.7  2220.7  536.422211.046     547 2207.46  559.32 2211.95   576.8 2216.38
   636.3 2218.99   682.6 2226.18   758.6 2224.77   781.7 2226.62   801.5 2230.52
     827 2237.91   875.7 2258.36   969.5 2280.17  1059.4 2312.44  1145.1  2339.6
  1181.4 2352.44    1264  2384.6  1303.7 2393.04  1320.2 2399.87    1367 2412.79
#Mann= 7 ,-1 , 0
       0      .1       0  536.42    .045       0  559.32      .1       0
  606.45     .05       0  668.53      .1       0  840.06     .05       0
 1180.64      .1       0
Bank Sta=536.42,559.32
XS Rating Curve= 0 ,0
Exp/Cntr=0.3,0.1
LCMann Table=0

Chan Stop Cuts=-1
Use User Specified Reach Order=0
Composite Channel Slope=5